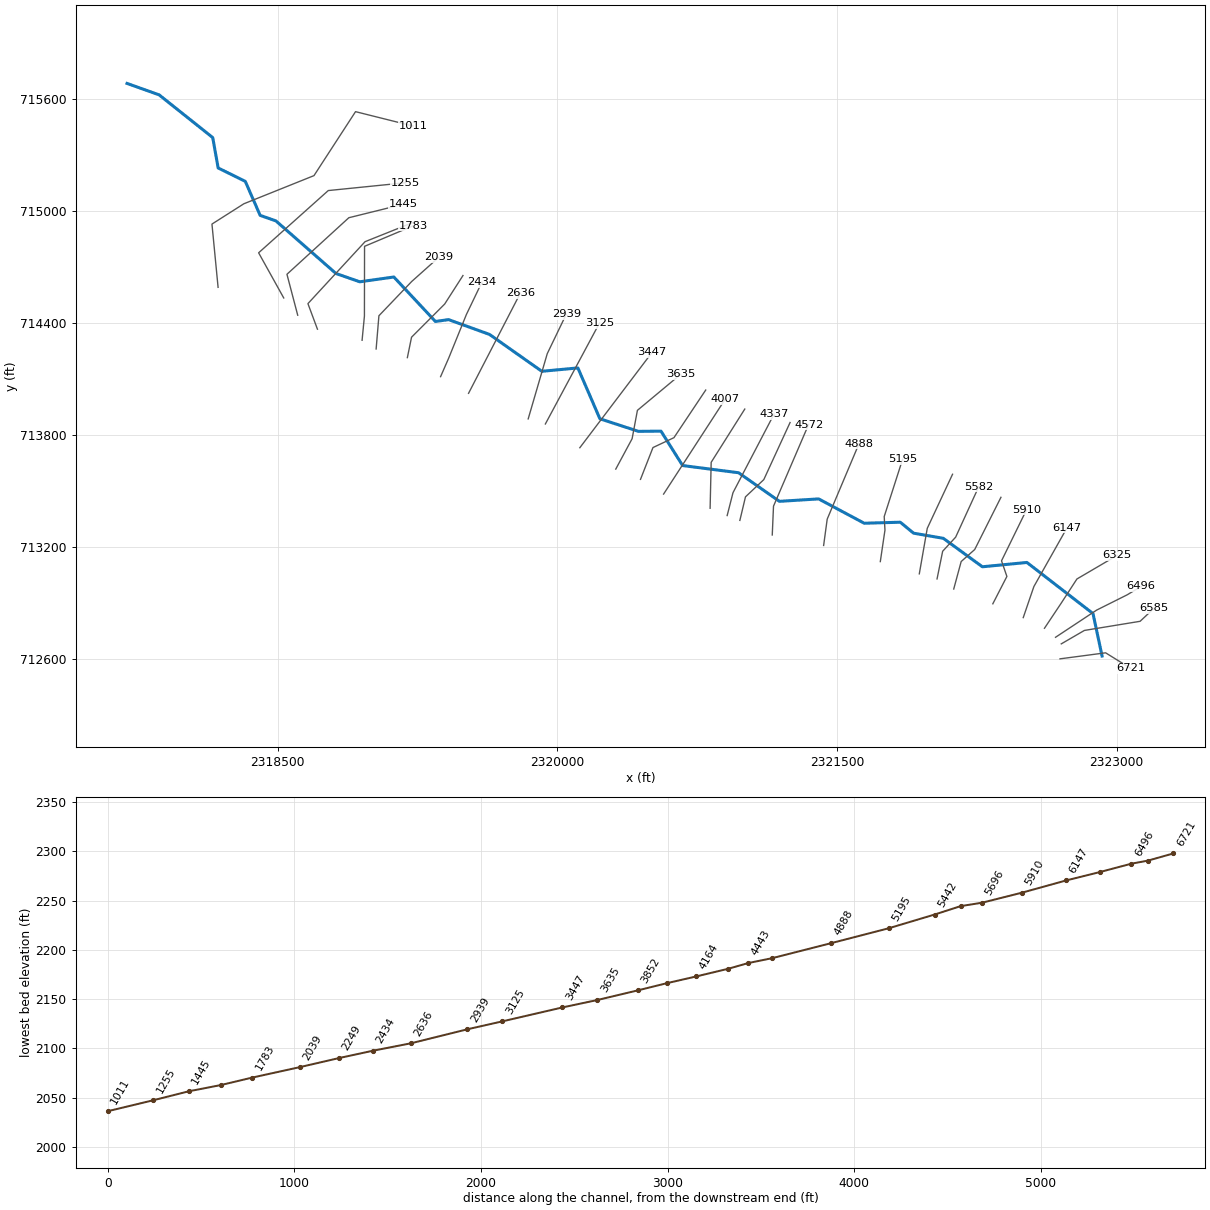
--- JOHNSRN.prj (project) ---

Proj Title=JOHNSRN
Current Plan=p01
Default Exp/Contr=0,0
English Units
Geom File=g01
Flow File=f01
Plan File=p01
BEGIN DESCRIPTION:
----------MODEL BY WOOD PLC 2022----------
AFH study
Randolph County, WV
HEC-RAS Version: RAS 6.2
Vertical Datum: NAVD88
Projection: NAD 1983 StatePlane West Virginia S FIPS 4702 (US Feet)
Terrain: 1-meter LIDAR (FEMA Region III 3DEP collected 2016-2018)
Land Use: 2019 NLCD
Hydrologic Method:
WV SIR2010-5033 regression equations
Additional Model Notes:
None
END DESCRIPTION:
DSS File=dss
DSS Export Rating Curves= 0
DSS Export Rating Curve Sorted= 0
DSS Export Volume Flow Curves= 0
DXF OffsetX= 0
DXF OffsetY= 0
DXF ScaleX= 0
DXF ScaleY= 0

--- JOHNSRN.p01 (plan) ---

Plan Title=Floodplain
Program Version=6.20
Short Identifier=Floodplain
Geom File=g01
Flow File=f01
Subcritical Flow
K Sum by GR= 0
Std Step Tol= 0.01
Critical Tol= 0.01
Num of Std Step Trials= 20
Max Error Tol= 0.3
Flow Tol Ratio= 0.001
Split Flow NTrial= 30
Split Flow Tol= 0.02
Split Flow Ratio= 0.02
Log Output Level= 0
Friction Slope Method= 1
Unsteady Friction Slope Method= 2
Unsteady Bridges Friction Slope Method= 1
Parabolic Critical Depth
Global Vel Dist= 0 , 0 , 0
Global Log Level= 0
CheckData=True
Encroach Param=-1 ,0,0, 0
Computation Interval=0.1SEC
Output Interval=1SEC
Instantaneous Interval=Max Profile
Mapping Interval=1HOUR
Computation Time Step Use Courant=        0
Computation Time Step Use Time Series=    0
Computation Time Step Count To Double=0
Computation Time Step Max Doubling=0
Computation Time Step Max Halving=0
Computation Time Step Residence Courant=0
Run HTab= 0
Run UNet= 0
Run Sediment= 0
Run PostProcess= 0
Run WQNet= 0
Run RASMapper=-1
UNET Theta= 0
UNET Theta Warmup= 0
UNET ZTol= 0
UNET ZSATol= 0
UNET MxIter= 0
UNET Max Iter WO Improvement= 0
UNET MaxInSteps= 0
UNET DtIC= 0
UNET DtMin= 0
UNET MaxCRTS= 0
UNET WFStab= 0
UNET SFStab= 0
UNET WFX= 1
UNET SFX= 1
UNET Gravity=32.174
UNET 1D Methodology=Finite Difference
UNET DSS MLevel= 1
UNET Pardiso=0
UNET DZMax Abort= 0
UNET Use Existing IB Tables= 0
UNET Froude Reduction=False
UNET Froude Limit= 0
UNET Froude Power= 0
UNET D1 Cores= 0
UNET WindReference=Eulerian
UNET WindDragFormulation=Hsu (1988)
UNET D2 Coriolis=0
UNET D2 Cores= 0
UNET D2 Theta= 1
UNET D2 Theta Warmup= 1
UNET D2 Z Tol= 0.01
UNET D2 Volume Tol= 0.01
UNET D2 Max Iterations= 20
UNET D2 Equation= 0
UNET D2 RampUpFraction=0.1
UNET D2 TimeSlices= 1
UNET D2 Turbulence Formulation=Non-Conservative (original)
UNET D2 Eddy Viscosity=0.3
UNET D2 Transverse Eddy Viscosity=0.1
UNET D2 Smagorinsky Mixing=0
UNET D2 BCVolumeCheck=0
UNET D2 Cores=0
UNET D2 SolverType=PARDISO (Direct)
UNET D2 Minimum Iterations= 2147483647
UNET D2 Maximum Iterations= 2147483647
UNET D2 Restart Number= 10
UNET D2 Relaxation Coeff=1.3
UNET D2 SOR Precondition Iterations= 10
UNET D2 ILUT Maximum Fill= 8
UNET D2 ILUT Tolerance=1E-08
UNET D1D2 MaxIter= 0
UNET D1D2 ZTol=0.01
UNET D1D2 QTol=0.1
UNET D1D2 MinQTol=1
DSS File=dss
Write IC File= 0
Write IC File at Fixed DateTime=0
Write IC File at Sim End=0
Echo Input=False
Echo Parameters=False
Echo Output=False
Write Detailed= 0
HDF Write Warmup=0
HDF Write Time Slices=0
HDF Flush=0
HDF Compression= 1
HDF Chunk Size= 1
HDF Spatial Parts= 1
HDF Use Max Rows=0
HDF Fixed Rows= 1
Calibration Method= 0
Calibration Iterations= 20
Calibration Max Change=0.05
Calibration Tolerance=0.2
Calibration Maximum=1.5
Calibration Minimum=0.5
Calibration Optimization Method= 1
WQ AD Non Conservative
WQ ULTIMATE=-1
WQ Max Comp Step=1HOUR
WQ Output Interval=15MIN
WQ Output Selected Increments= 0
WQ Output face flow=0
WQ Output face velocity=0
WQ Output face area=0
WQ Output face dispersion=0
WQ Output cell volume=0
WQ Output cell surface area=0
WQ Output cell continuity=0
WQ Output cumulative cell continuity=0
WQ Output face conc=0
WQ Output face dconc_dx=0
WQ Output face courant=0
WQ Output face peclet=0
WQ Output face adv mass=0
WQ Output face disp mass=0
WQ Output cell mass=0
WQ Output cell source sink temp=0
WQ Output nsm pathways=0
WQ Output nsm derived pathways=0
WQ Create Restart=0
WQ Fixed Restart=0
WQ System Summary=0
WQ Write To DSS=0
Sorting and Armoring Iterations= 10
XS Update Threshold= 0.02
Bed Roughness Predictor= 0
Hydraulics Update Threshold= 0.02
Energy Slope Method= 1
Volume Change Method= 1
Sediment Retention Method= 0
Sediment TS Multiplier= 1
Warm Up Method= 0
XS Weighting Method= 0
Number of US Weighted Cross Sections= 1
Number of DS Weighted Cross Sections= 1
Upstream XS Weight=0
Main XS Weight=1
Downstream XS Weight=0
Number of DS XS's Weighted with US Boundary= 1
Upstream Boundary Weight= 1
Weight of XSs Associated with US Boundary= 0
Number of US XS's Weighted with DS Boundary= 1
Downstream Boundary Weight= 0.5
Weight of XSs Associated with DS Boundary= 0.5
Percentile Method= 0
Sediment Output Level= 3
Mass or Volume Output= 0
Output Increment Type= 1
Profile and TS Output Increment= 1
Transport Output Increment 1
XS Output Flag= 0
XS Output Increment= 10
Read HDF5 Sediment Hotstart= 0
Sediment Hotstart Type= 0
Write Gradation File= 0
Read Gradation Hotstart= 0
Write HDF5 File= 1
Write Binary Output= 1
Write DSS Sediment File= 0
DSS Sediment Output Type= 1
SV Curve= 0
Specific Gage Flag= 0
Subcell Erosion Methods= 0
Subcell Deposition Methods= 0
Advection Scheme= 1
Matrix Solver= 0
Implicit Weighting Factor= 1
Maximum Outer Loop Convergence Iterations= 5
Convergence Maximum Absolute= 0.001
Convergence RMSE= 0.0001
Grain Fractions Max Abs Error= 0.001
Max Subgrid Regions= 1
Max Subgrid Length Scale= 3.402823E+38
Initial Layer Thickness= 3.402823E+38
Min Layer Thickness= 3.402823E+38
Max Layer Thickness= 3.402823E+38
Number of Layers= 5

--- JOHNSRN.f01 (steady flow) ---

Flow Title=Flow
Program Version=6.20
Number of Profiles= 1
Profile Names=P100yr
River Rch & RM=JOHNSRN,Main            ,6721
     390
River Rch & RM=JOHNSRN,Main            ,4007
     435
Boundary for River Rch & Prof#=JOHNSRN,Main            , 1
Up Type= 0
Dn Type= 3
Dn Slope=0.0364
DSS Import GetInterval= 0
DSS Import GetPeak= 0
DSS Import FillOption= 0

--- JOHNSRN.g01 (geometry) ---

Geom Title=Geometry
Program Version=6.20

River Reach=JOHNSRN         ,Main
Reach XY= 30
     2322922.147       712613.82     2322873.536       712841.25
     2322518.935      713115.382     2322280.133      713092.205
     2322070.237      713244.809     2321911.383      713272.153
     2321839.508      713331.007     2321646.279      713325.538
     2321401.748      713456.007     2321191.331      713442.986
 2320972.1475513713596.198551304     2320672.147       713634.74
     2320556.175      713819.115     2320434.994      713818.073
     2320228.397      713885.434     2320110.342      714158.004
     2319916.939      714139.948     2319636.383      714337.517
     2319416.823      714416.858     2319345.989      714407.136
     2319123.073       714645.33     2318940.434      714619.635
     2318812.696      714664.029     2318490.387      714946.147
     2318406.012      714975.661     2318326.151      715157.953
     2318180.665      715229.828     2318151.498      715392.675
     2317863.824      715621.755     2317691.773      715682.994

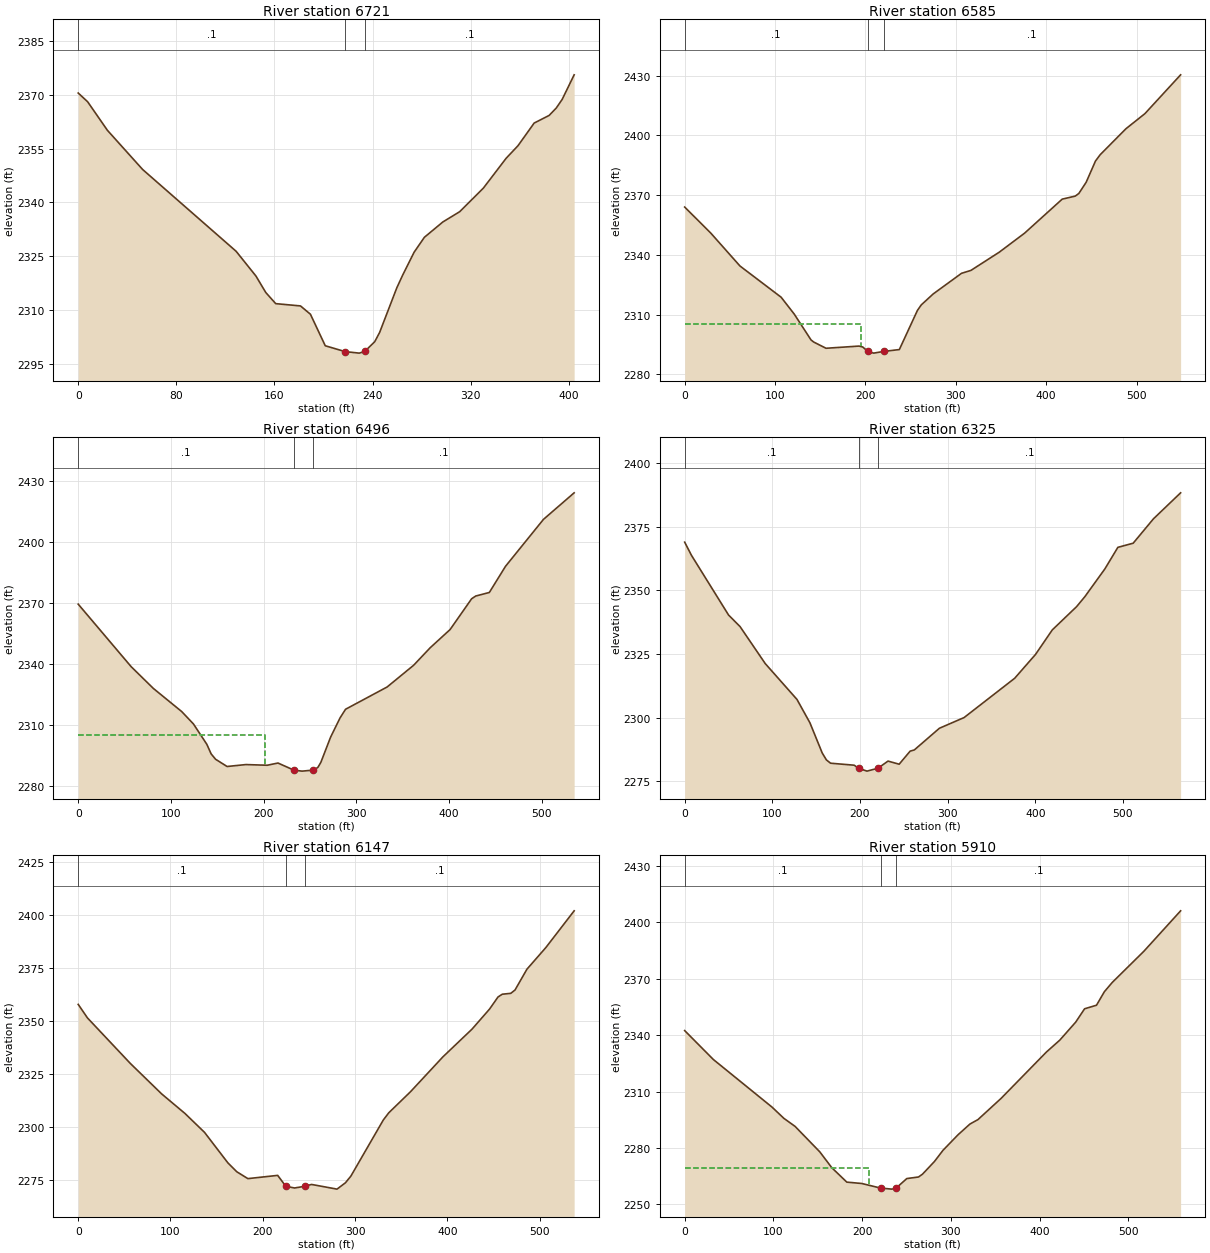
Type RM Length L Ch R = 1 ,6721    ,136.4,136.5,136.8
XS GIS Cut Line= 3
2322696.54769942 712598.750564222322941.16977219712630.993588424
2323075.10400998712548.034321728
#Sta/Elev= 30
       0 2370.53     7.7 2368.09    23.8 2360.13    52.5  2349.2   128.7 2326.38
   144.9 2319.46   152.9 2314.87     161 2311.76   181.2 2311.12   189.3 2308.81
   201.4 2300.01   217.5 2298.38   229.1 2297.95   233.6 2298.43   241.7 2301.13
   245.7  2303.7   259.7 2316.15   264.4 2319.64   273.8 2326.09   282.2 2330.27
   297.3 2334.56     311 2337.42   330.3    2344   348.9 2352.34   358.5 2355.82
   371.7 2362.15   383.9 2364.28   389.7 2366.34   394.5 2368.73   404.3 2375.61
#Mann= 3 ,-1,0
       0      .1       0   217.5    .045       0   233.6      .1       0
Bank Sta=217.5,233.6
XS Rating Curve= 0 ,0
Exp/Cntr=0.3,0.1

Type RM Length L Ch R = 1 ,6585    ,85.7,88.5,94.2
XS GIS Cut Line= 4
2322703.28657371712678.9700318142322827.22571913  712750.9346969
2323126.07898109712799.9106495282323201.04217388712869.876296139
#Sta/Elev= 30
       0 2363.98    28.8 2350.94    61.2 2334.37   106.7 2318.71   121.3 2310.18
   139.8 2297.25   142.7 2296.21   156.4 2293.07   192.9 2294.17     197 2293.71
  202.622291.481   209.1 2290.63  220.25 2291.49   237.5 2292.42   257.5 2312.07
   261.8 2314.87     275 2320.36   306.3 2330.71   316.7 2332.17   348.1 2341.33
     376 2350.84   417.7 2367.95   432.1 2369.47   436.1  2370.8   444.2 2376.42
   454.5 2387.08   459.7 2390.25   488.2  2403.3   509.2 2410.88   548.7 2430.37
#Mann= 3 ,0,0
       0      .1       0  202.62    .045       0  220.25      .1       0
#XS Ineff= 2 , 0
          194.54 2305.38
Permanent Ineff=
       F       F
Bank Sta=202.62,220.25
XS Rating Curve= 0 ,0
Exp/Cntr(USF)=0,0
Exp/Cntr=0.3,0.1

Type RM Length L Ch R = 1 ,6496    ,169.7,171.1,178
XS GIS Cut Line= 4
2322672.49922128712714.2654588322322892.74131329712859.807593955
2323056.57825662712941.7764071072323132.01199837712986.737724261
#Sta/Elev= 30
       0 2369.54    57.1 2338.84    81.1 2328.13   111.6  2316.8   124.3  2310.7
   138.7 2300.74   143.4 2295.99   148.2 2293.35   160.6 2289.79   180.9 2290.74
   203.9 2290.41   215.5  2291.5   232.8 2287.98   241.5 2287.52   253.7 2288.01
   258.5 2289.33   261.7 2291.77   272.3 2304.25   282.5 2313.69   288.4 2317.91
   333.2 2328.84   361.8 2339.51   379.6 2348.08   401.2 2357.08   424.4 2372.19
   428.8 2373.53   443.5 2375.28     461 2388.16   501.9 2411.19     535 2424.23
#Mann= 3 ,0,0
       0      .1       0   232.8    .045       0   253.7      .1       0
#XS Ineff= 2 , 0
          201.87  2305.1
Permanent Ineff=
       F       F
Bank Sta=232.8,253.7
XS Rating Curve= 0 ,0
Exp/Cntr(USF)=0,0
Exp/Cntr=0.3,0.1

Type RM Length L Ch R = 1 ,6325    ,177.7,178.4,179
XS GIS Cut Line= 4
2322613.15157874712762.6548360472322701.11495529712894.422685759
2322787.24534964713026.7279508112323002.50316892713152.866290773
#Sta/Elev= 30
       0 2368.94     7.8 2363.73    50.1 2340.28    63.1 2335.79    91.9 2321.22
   128.1 2307.13   142.9 2297.94   156.9 2286.09   161.7 2283.34   166.5 2282.05
   193.4 2281.27   198.4 2280.07     208 2278.94   220.5 2280.08     232 2282.88
   244.7 2281.66   257.2 2286.79     262 2287.27   290.6 2295.79   318.8    2300
   376.5 2315.44   400.3 2324.82   419.4 2334.45   447.2 2343.62   456.5 2347.49
   479.4 2358.43   494.2  2366.9   511.7 2368.53   534.8 2378.11   565.8 2388.33
#Mann= 3 ,-1,0
       0      .1       0   198.4    .045       0   220.5      .1       0
Bank Sta=198.4,220.5
XS Rating Curve= 0 ,0
Exp/Cntr(USF)=0,0
Exp/Cntr=0.3,0.1

Type RM Length L Ch R = 1 ,6147    ,228.5,237.3,243.7
XS GIS Cut Line= 3
2322499.32087799712819.6965450062322556.29285492712986.063566737
2322733.99439822713301.011465371
#Sta/Elev= 30
       0 2357.74      10 2351.36    56.5 2329.85    90.4 2315.49   115.7 2306.24
   136.9 2297.32   162.2 2282.93   171.9 2278.71   183.9 2275.48   216.2 2277.01
     225 2271.86   234.5 2271.06   245.6 2271.87   252.9 2272.73   280.5 2270.52
   289.6 2273.51   295.5 2276.66   330.7 2303.18   336.6 2306.56   360.1 2316.48
   395.3 2332.98   426.8 2346.04   445.8 2355.51     455 2361.23   459.6 2362.53
   468.8 2362.95   473.4 2364.51   486.3 2374.32   506.9  2384.6   537.5  2401.9
#Mann= 3 ,-1,0
       0      .1       0     225    .045       0   245.6      .1       0
Bank Sta=225,245.6
XS Rating Curve= 0 ,0
Exp/Cntr(USF)=0,0
Exp/Cntr=0.3,0.1

Type RM Length L Ch R = 1 ,5910    ,222.7,213.3,201.6
XS GIS Cut Line= 4
2322336.16367739712893.7342662872322411.57246758713040.438639938
2322382.78002042713124.0738436082322517.14477385713398.287626132
#Sta/Elev= 30
       0 2342.42    32.3 2327.05    98.3 2301.77   111.8 2295.74   124.4 2291.47
   152.3  2277.9   165.7 2269.52   182.7 2261.82   199.6 2261.09   220.7 2258.66
   233.4  2258.1   238.1 2258.61   250.3 2263.72   263.5 2264.56     268 2266.07
   281.4 2272.78   291.1 2278.77   308.1 2287.05   321.4 2292.71   330.4 2295.06
   356.6  2306.4   407.7 2331.07   422.7 2337.36   440.6 2346.93   450.6 2354.02
     464 2355.91   472.9  2363.1   481.8 2368.04   517.4 2384.61   558.8 2406.12
#Mann= 3 ,0,0
       0      .1       0   220.7    .045       0   238.1      .1       0
#XS Ineff= 2 , 0
          207.66 2269.46
Permanent Ineff=
       F       F
Bank Sta=220.7,238.1
XS Rating Curve= 0 ,0
Exp/Cntr(USF)=0,0
Exp/Cntr=0.3,0.1

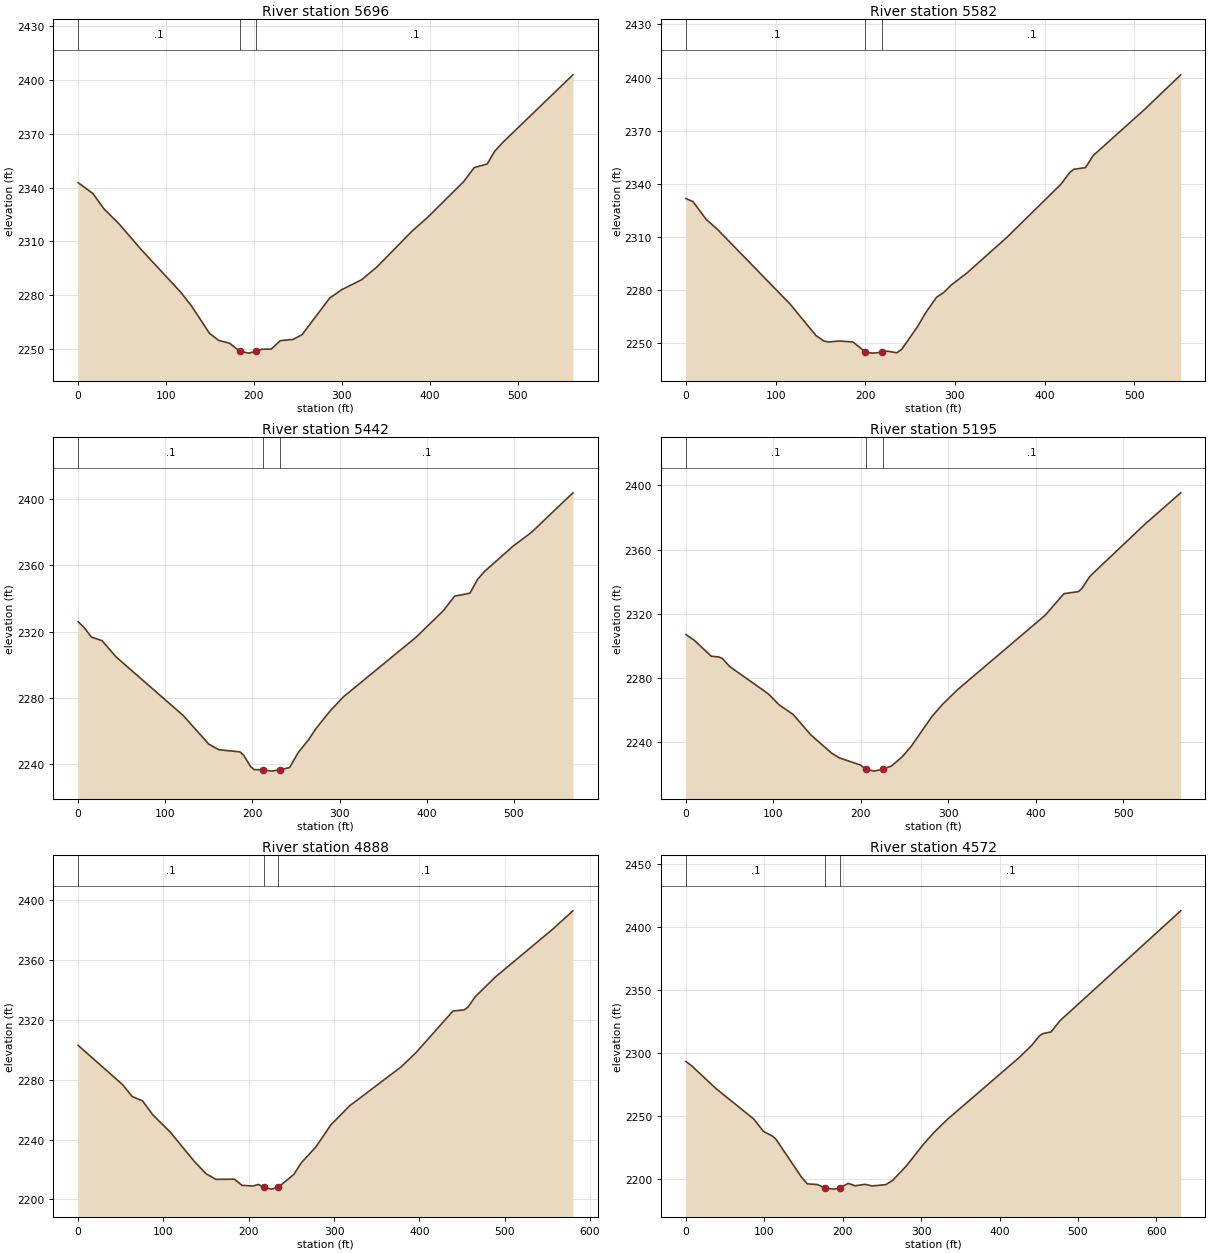
Type RM Length L Ch R = 1 ,5696    ,114,114.6,115.8
XS GIS Cut Line= 4
2322126.40550149712972.9449367852322166.32834733713120.251105072
 2322238.9949997713184.6913439652322379.68229476713464.486553931
#Sta/Elev= 30
       0  2342.7    16.8 2336.65    29.3 2328.16    47.3 2319.38    70.7 2306.05
   116.3 2282.01   128.7 2274.37   149.4 2258.96     160 2254.97   172.1 2253.49
   184.2  2248.9   194.3 2247.93   202.8 2248.95   208.6 2250.07   219.8 2250.19
   229.9 2254.86   244.5 2255.54   254.8 2258.19   286.1 2278.49   299.5 2283.09
   322.5 2288.72   340.4 2296.05   380.1 2315.86     397 2323.11   438.7 2343.32
   450.6 2351.04   465.5 2353.12   474.1 2360.26   483.1 2365.04   562.9 2402.64
#Mann= 3 ,-1,0
       0      .1       0   184.2    .045       0   202.8      .1       0
Bank Sta=184.2,202.8
XS Rating Curve= 0 ,0
Exp/Cntr=0.3,0.1

Type RM Length L Ch R = 1 ,5582    ,135.8,139.8,146.7
XS GIS Cut Line= 4
2322036.91586791 713027.110099082322066.99964165713175.327716043
2322136.70594666713250.9040256832322260.70979451713521.657989344
#Sta/Elev= 30
       0 2331.73     7.9    2330    22.5 2320.03    34.8 2314.51   116.4 2272.05
     145 2254.43   153.8 2251.35   158.9 2250.77   170.7 2251.35   186.4 2250.76
   200.2 2245.06   208.2 2244.48   219.1    2245   224.5 2245.61   235.4 2244.68
   240.8 2246.72   258.4  2259.5   267.4 2267.21   279.5 2275.99   287.4 2278.64
   296.2 2283.01   313.8 2289.86     358 2309.82   418.3 2339.81   428.1 2346.42
   432.5 2348.25   445.7 2349.18   454.5  2356.1   511.9 2382.15   551.9 2401.57
#Mann= 3 ,-1,0
       0      .1       0   200.2    .045       0   219.1      .1       0
Bank Sta=200.2,219.1
XS Rating Curve= 0 ,0
Exp/Cntr(USF)=0,0
Exp/Cntr=0.3,0.1

Type RM Length L Ch R = 1 ,5442    ,244.4,247.3,248.3
XS GIS Cut Line= 3
2321941.71007532 713054.235996212321984.43370474713298.211138637
2322120.10425757 713588.10380021
#Sta/Elev= 30
       0 2325.98       7 2322.39    15.2 2316.72    27.4 2314.56    43.6 2304.72
   120.8 2269.35   149.8 2252.24   161.4 2248.83   185.7 2247.54   189.8 2245.61
   197.9 2238.71     202 2236.84   212.1 2236.74   222.3 2235.93     232  2236.8
   242.6 2238.06   252.7 2247.23   264.2 2254.69     273 2261.61   288.8 2271.95
   304.2 2280.59   387.9 2316.66   418.8 2332.44     432 2341.34   449.7 2343.19
   458.5 2351.55   466.3 2356.21   499.4 2371.61   520.4 2379.88   567.8 2403.64
#Mann= 3 ,-1,0
       0      .1       0   212.1    .045       0     232      .1       0
Bank Sta=212.1,232
XS Rating Curve= 0 ,0
Exp/Cntr=0.3,0.1

Type RM Length L Ch R = 1 ,5195    ,309.9,306.1,301.3
XS GIS Cut Line= 4
2321732.53686064 713119.904611012321757.55855283713288.960656971
2321753.45938952713361.2687654912321852.10572282713668.295004602
#Sta/Elev= 30
       0 2306.99     9.4 2303.51      29 2293.52    37.7 2293.05    41.7 2292.08
    50.1 2287.07    94.3 2270.05   106.4 2263.29   122.6 2257.23   142.8 2244.52
   166.3 2233.26   175.1 2230.25   199.2  2225.8206.08162223.068   215.2 2221.92
   224.9 2223.07   235.2 2225.14   247.4 2230.89   257.6 2237.36     281 2255.72
   293.6 2263.64   310.4 2272.57   410.8 2319.03   432.3 2332.48   449.1  2333.8
   453.3 2336.07   461.6 2343.03   465.9 2345.34   524.7 2375.69   565.8 2395.33
#Mann= 3 ,-1,0
       0      .1       0206.0816    .045       0   224.9      .1       0
Bank Sta=206.0816,224.9
XS Rating Curve= 0 ,0
Exp/Cntr=0.3,0.1

Type RM Length L Ch R = 1 ,4888    ,317.7,316.7,316.8
XS GIS Cut Line= 3
2321428.51605723713206.3379783652321447.71102201713347.558076365
2321617.72356717713750.652336676
#Sta/Elev= 30
       0 2303.02      52 2276.86    63.4 2268.81    75.5 2265.91    87.6 2256.55
   107.8 2245.17   136.1 2225.54   150.2 2217.09   161.6 2213.47   183.3 2213.59
     192 2209.48   205.1 2209.02   211.3 2210.07   217.4 2208.25   226.8 2206.93
   234.8 2208.31   252.8 2216.72   261.5 2224.44   278.9 2235.28   296.2 2249.85
   317.9 2262.47   378.7 2288.66   396.1 2298.22   439.5 2326.03   452.5 2326.75
   456.8 2328.46   465.5 2335.52   489.1 2348.71   556.7 2380.88     580 2392.97
#Mann= 3 ,-1,0
       0      .1       0   217.4    .045       0   234.8      .1       0
Bank Sta=217.4,234.8
XS Rating Curve= 0 ,0
Exp/Cntr(USF)=0,0
Exp/Cntr=0.3,0.1

Type RM Length L Ch R = 1 ,4572    ,134.4,128.9,125.8
XS GIS Cut Line= 3
2321152.96110874713262.5327825242321159.63973049713416.972070446
2321347.82410414713854.652174582
#Sta/Elev= 30
       0 2293.17     6.7 2290.11    38.7 2271.46    86.7 2247.34    98.7 2237.67
   110.7 2233.72   114.8  2231.4   147.6 2200.98   154.8 2195.88   167.9 2195.28
   176.9 2192.61   188.6 2191.66   196.4 2192.64   206.9 2196.23   215.8 2194.33
   228.8 2195.48   237.5 2194.18     255 2195.25   263.7 2198.64   281.1 2210.11
   302.8 2227.24   316.5 2236.85   333.3 2247.06   424.8 2296.22   441.4 2306.29
   450.9 2313.62   455.2 2315.36   465.7 2316.71     477 2325.58     631 2413.04
#Mann= 3 ,-1,0
       0      .1       0   176.9    .045       0   196.4      .1       0
Bank Sta=176.9,196.4
XS Rating Curve= 0 ,0
Exp/Cntr=0.3,0.1

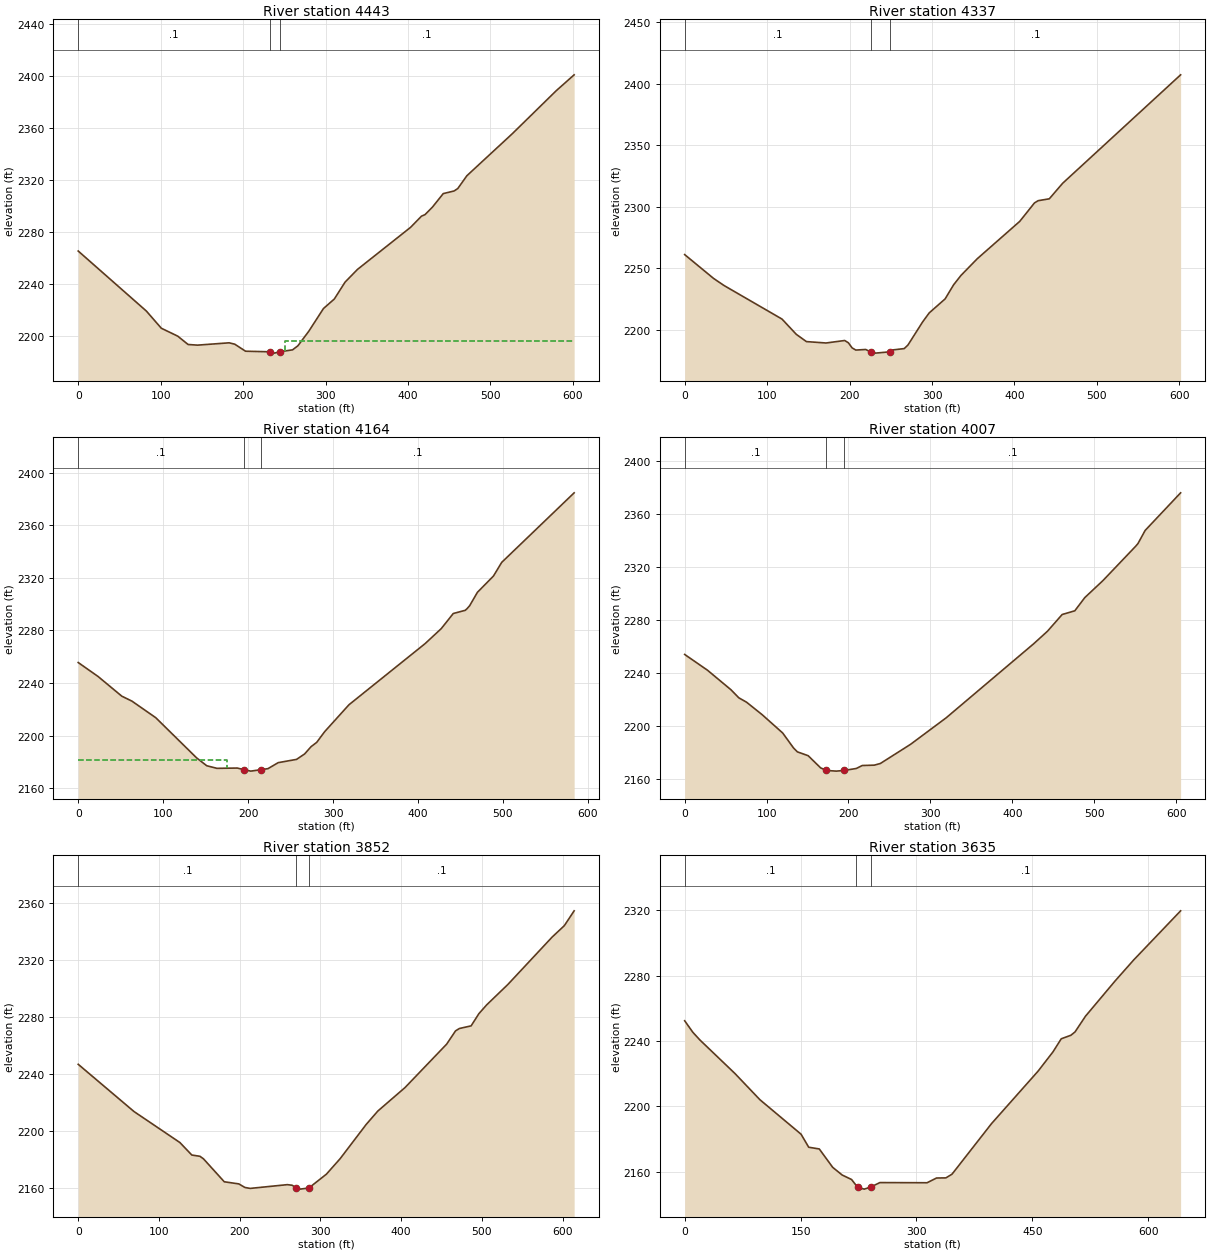
Type RM Length L Ch R = 1 ,4443    ,105.2,105.9,108.7
XS GIS Cut Line= 4
2320979.21675624 713340.755746342321009.30052998713466.960845932
2321107.62310757713559.4134188892321248.50321874 713865.38741034
#Sta/Elev= 30
       0 2265.18    82.7 2219.01   100.8 2205.81   120.7 2199.74   133.3 2193.31
   144.7 2192.81   183.1  2194.6   189.9 2193.54     203 2188.14   232.5  2187.7
     238 2186.67  244.19 2187.71     260 2189.19   266.5 2192.32   279.9 2203.67
   297.5 2220.96   310.7 2228.29   323.7 2241.26   338.8 2251.06   403.2 2283.41
   416.4 2291.98   420.8 2293.23   429.6 2298.88   442.8 2309.33     456 2311.37
   460.4 2313.21   471.5 2323.09   526.5 2355.34     580 2388.54   601.6 2400.67
#Mann= 3 ,0,0
       0      .1       0   232.5    .045       0  244.19      .1       0
#XS Ineff= 2 , 0
                           251.1         2195.76
Permanent Ineff=
       F       F
Bank Sta=232.5,244.19
XS Rating Curve= 0 ,0
Exp/Cntr(USF)=0,0
Exp/Cntr=0.3,0.1

Type RM Length L Ch R = 1 ,4337    ,168.1,173.2,178.5
XS GIS Cut Line= 3
2320911.09047702713366.7307252622320942.37015339713489.361302438
2321162.44971661713910.299841274
#Sta/Elev= 30
       0 2261.04    35.1 2241.65    47.9 2235.85   118.1 2208.62   135.4 2196.22
   147.7 2190.32   171.5 2189.19   194.1 2191.21   198.6 2189.35   203.1 2185.21
   207.6 2183.44   219.6 2183.91   225.7 2181.93   231.5 2180.95   249.3 2182.04
   252.7 2183.57   266.3 2184.64   270.8 2187.49   288.8 2206.47   296.7 2213.69
   315.9 2225.01   326.3 2236.56   335.2 2244.14   354.9 2257.67   406.4 2288.02
   424.3 2303.03   428.8 2304.88   442.3 2306.39   458.5 2319.02   601.6 2407.18
#Mann= 3 ,-1,0
       0      .1       0   225.7    .045       0   249.3      .1       0
Bank Sta=225.7,249.3
XS Rating Curve= 0 ,0
Exp/Cntr=0.3,0.1

Type RM Length L Ch R = 1 ,4164    ,162.9,157.2,151
XS GIS Cut Line= 3
2320819.60408247713405.8842711652320825.31103142713652.098354348
2321005.48756249713937.445801745
#Sta/Elev= 30
       0 2255.62    23.3 2245.05    51.3 2230.05    63.3 2226.26    91.3 2213.67
   139.3 2183.19   151.3 2177.16   163.3 2175.19   187.3 2175.41   195.4 2174.11
   203.2 2173.07   215.12174.164   223.4 2174.96   235.4 2179.51     257 2181.99
   266.5 2186.11   274.1 2191.66   280.7  2194.9   290.1 2203.05   318.7 2223.51
   408.4 2270.02   427.3 2281.35   441.5 2292.88   455.7 2295.34   457.9 2296.68
   460.8 2298.81   469.9 2308.97   488.8 2321.35   498.5 2331.74   583.8 2384.62
#Mann= 3 ,-1,0
       0      .1       0   195.4    .045       0   215.1      .1       0
#XS Ineff= 2 , 0
          175.33 2181.72
Permanent Ineff=
       F       F
Bank Sta=195.4,215.1
XS Rating Curve= 0 ,0
Exp/Cntr(USF)=0,0
Exp/Cntr=0.3,0.1

Type RM Length L Ch R = 1 ,4007    ,160.1,154.1,148
XS GIS Cut Line= 2
2320570.02983383713481.7885146172320899.94359821713989.520206238
#Sta/Elev= 30
       0 2254.17    27.9 2242.27    56.5 2227.57    66.1 2221.49    75.6 2218.17
    94.7 2208.72   119.7 2194.96   132.8 2183.77   137.6 2180.76   150.8 2177.86
   165.9 2168.74   172.8 2166.73   185.3 2166.24   194.8 2166.78   209.5 2168.23
   216.8 2170.47   231.5 2170.74   238.9 2171.99   275.8 2186.44   319.2 2206.39
   426.2 2262.28   442.9 2271.64   460.9 2284.29   476.3 2287.06   488.5 2297.01
   510.5 2309.74   550.5 2335.63   553.4 2337.71   562.2 2347.64   605.5 2375.98
#Mann= 3 ,-1,0
       0      .1       0   172.8    .045       0   194.8      .1       0
Bank Sta=172.8,194.8
XS Rating Curve= 0 ,0
Exp/Cntr(USF)=0,0
Exp/Cntr=0.3,0.1

Type RM Length L Ch R = 1 ,3852    ,209.3,217.4,223.8
XS GIS Cut Line= 4
2320446.20656559 713560.787171182320513.05939612713731.180361198
2320625.56781824713784.1734585722320795.96100826714039.355604387
#Sta/Elev= 30
       0 2246.65    69.2 2213.44   125.9 2191.74   140.7 2182.95   150.8 2182.05
   155.1 2180.31   180.9 2164.17   198.9 2162.68   206.5 2160.17     213 2159.52
     259 2162.15     265 2161.73  270.15 2159.82   274.9 2159.01   285.7 2159.83
   307.4 2169.53   324.4 2180.39   356.7 2204.46   371.1 2213.84   404.8 2230.35
   456.2 2260.74   467.3  2270.1   472.1 2271.79   486.6 2273.63   496.2 2282.18
   505.8 2288.33   532.1 2302.69   586.9 2335.95     602 2343.96   614.2  2354.4
#Mann= 3 ,0,0
       0      .1       0  270.15    .045       0   285.7      .1       0
Bank Sta=270.15,285.7
XS Rating Curve= 0 ,0
Exp/Cntr(USF)=0,0
Exp/Cntr=0.3,0.1

Type RM Length L Ch R = 1 ,3635    ,191.9,188,183.1
XS GIS Cut Line= 4
2320313.56182402713615.8098962932320401.21016471713778.663931785
2320429.63213291713930.6465667542320661.95317521714124.036022646
#Sta/Elev= 30
       0 2252.37    10.6 2245.29    19.7  2240.6    65.2 2219.98    97.4 2203.98
   150.6 2182.87   160.5 2174.88   174.2 2173.82   191.6 2162.54   203.8 2157.86
     216 2155.09  222.182151.326   223.9 2150.41   232.3 2149.21  240.55 2150.43
   252.6 2153.22   313.7 2153.12   325.9 2156.02   338.1  2156.1     346 2158.39
   397.1 2189.35   457.4 2221.53   476.7 2233.36   487.3 2241.32   499.8 2243.49
   505.1  2245.5   518.6  2255.1     557 2276.75   581.1 2289.64   641.8 2319.73
#Mann= 3 ,-1,0
       0      .1       0  222.18    .045       0  240.55      .1       0
Bank Sta=223.9,240.55
XS Rating Curve= 0 ,0
Exp/Cntr(USF)=0,0
Exp/Cntr=0.3,0.1

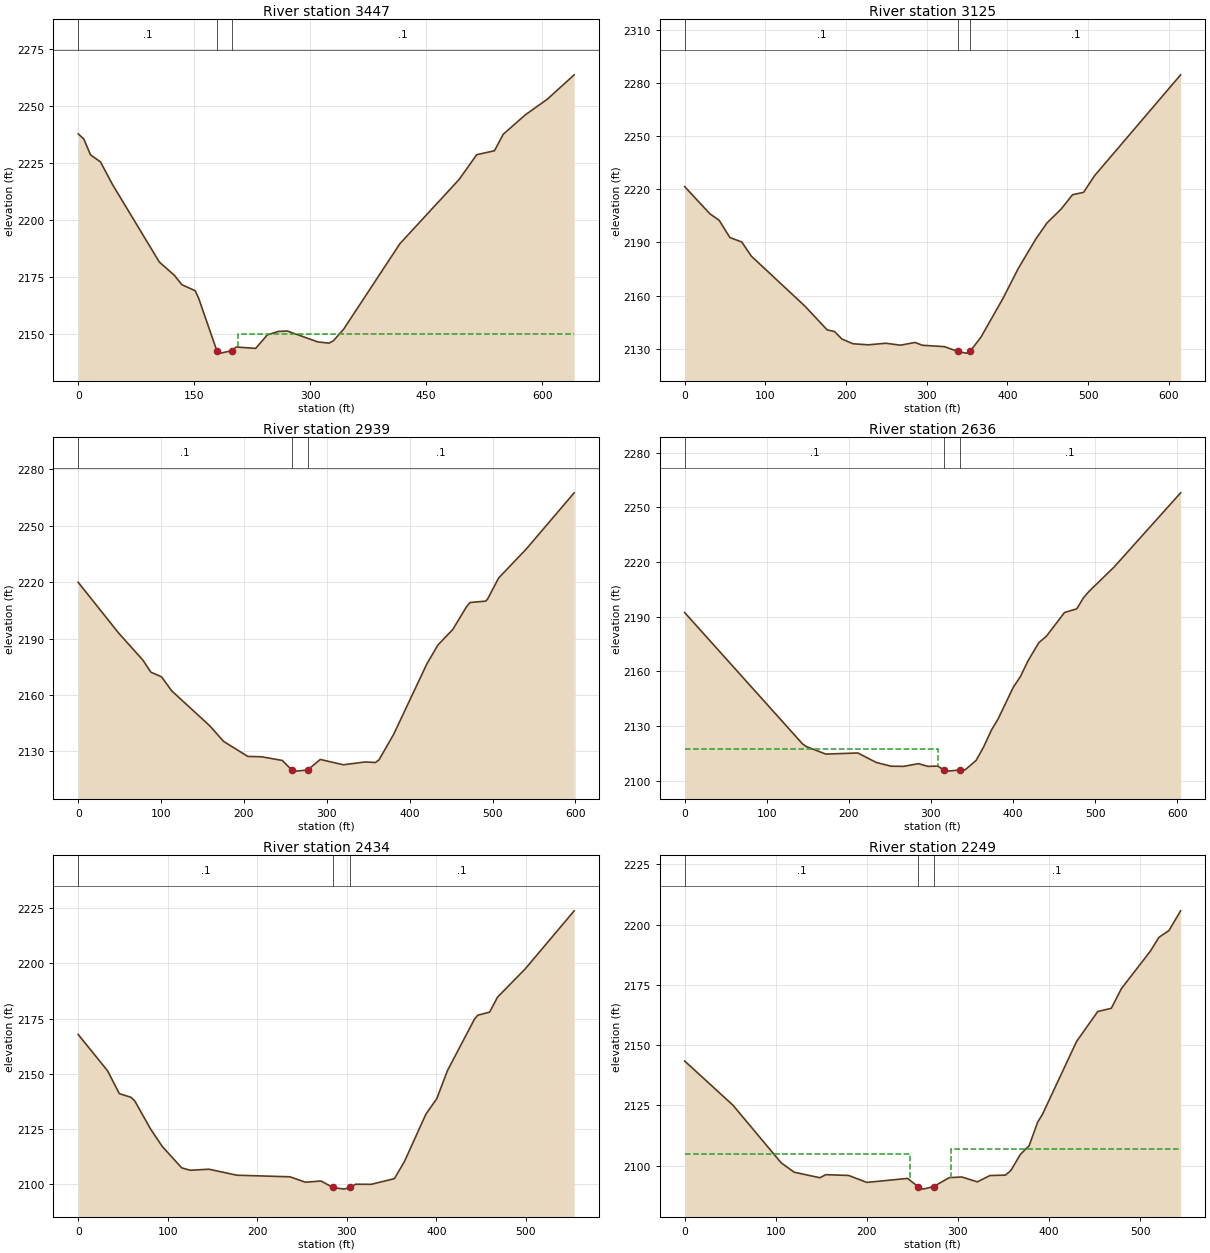
Type RM Length L Ch R = 1 ,3447    ,321.2,321.6,321
XS GIS Cut Line= 2
2320120.76545631713730.3156155342320508.38864272714241.504271845
#Sta/Elev= 30
       0 2237.77     7.3  2235.5    15.9 2228.58    28.7 2225.53    44.4 2215.54
   104.9 2181.59   124.4 2175.76   134.1 2171.62   151.3 2169.01   155.8  2165.7
   179.3  2142.7   184.4 2141.63   198.6 2142.72   204.4 2144.32   229.5  2143.7
   244.6 2149.61   258.6 2151.13   270.4 2151.34   309.8 2146.56   324.2    2146
     330 2147.02   343.3 2152.11   416.1 2189.62   492.7 2217.78   515.5 2228.65
   538.4 2230.36   549.8 2237.61   578.3  2246.1   606.9    2253   641.5 2263.66
#Mann= 3 ,-1,0
       0      .1       0   179.3    .045       0   198.6      .1       0
#XS Ineff= 2 , 0
                          206.52         2150.09
Permanent Ineff=
       F       F
Bank Sta=179.3,198.6
XS Rating Curve= 0 ,0
Exp/Cntr(USF)=0,0
Exp/Cntr=0.3,0.1

Type RM Length L Ch R = 1 ,3125    ,185.6,186.8,186.4
XS GIS Cut Line= 2
2319935.92439517713857.5547004872320226.52274666714399.207279447
#Sta/Elev= 30
       0 2221.53    31.3 2206.17    42.8 2202.49      56 2192.81    70.8 2190.25
    82.6  2182.3   149.4  2153.9   176.6 2140.64   185.7 2139.72   194.8 2135.52
   208.4 2132.84   227.4  2132.2   249.2  2133.1   267.4 2132.01   285.6 2133.54
   294.6 2131.96   321.9 2131.19  338.74 2128.44   349.1 2127.52   353.6 2128.45
   367.3  2136.6   394.5  2158.4   413.5 2175.34   435.3 2192.01     449    2201
   466.7  2208.9   480.7 2216.96   494.4 2218.29     508 2227.68   614.7 2284.65
#Mann= 3 ,0,0
       0      .1       0  338.74    .045       0   353.6      .1       0
Bank Sta=338.74,353.6
XS Rating Curve= 0 ,0
Exp/Cntr(USF)=0,0
Exp/Cntr=0.3,0.1

Type RM Length L Ch R = 1 ,2939    ,303,302.8,299.3
XS GIS Cut Line= 3
2319843.72966201713884.7970420162319945.98956087  714234.4392381
2320047.69663316714445.285451515
#Sta/Elev= 30
       0 2219.93      49 2192.83    78.1 2178.52    87.7 2172.13   100.4 2169.71
   112.9 2162.17   158.8 2143.58   175.4 2135.32   204.6 2127.33   221.3 2127.13
   246.3 2125.17  257.62 2120.12     263  2119.5   276.8 2120.11   292.1 2125.71
   319.9 2122.87   346.3 2124.38   358.6 2124.09     363 2125.53   380.7 2139.15
   420.6 2176.46   433.9 2186.52   451.9 2194.82   468.4 2206.85   472.8 2209.19
   491.7 2209.94   493.8 2210.92   507.4 2222.29   540.5 2237.58   598.4 2267.53
#Mann= 3 ,0,0
       0      .1       0  257.62    .045       0   276.8      .1       0
Bank Sta=257.62,276.8
XS Rating Curve= 0 ,0
Exp/Cntr(USF)=0,0
Exp/Cntr=0.3,0.1

Type RM Length L Ch R = 1 ,2636    ,200.4,202.2,202.2
XS GIS Cut Line= 2
 2319523.8135824714021.9039332782319801.41272026714558.482754637
#Sta/Elev= 30
       0 2192.32   143.3 2120.34   147.8 2118.83   171.9 2114.62   210.9 2115.24
   233.4 2110.03   251.4 2107.97   266.9 2107.89   284.7 2109.37   296.5 2107.88
   308.4 2108.04  315.722105.866   320.3 2105.27   335.1 2105.89   341.5 2105.96
     355 2111.16     364 2118.41   373.7 2127.83     382 2134.11     400 2151.06
     409 2157.24   418.2  2165.8   431.5 2175.86   440.5 2179.26   462.7 2192.37
   477.6 2194.36   485.6 2200.32   492.4 2203.89   523.1 2217.33   604.1 2258.05
#Mann= 3 ,-1,0
       0      .1       0  315.72    .045       0   335.1      .1       0
#XS Ineff= 2 , 0
          308.81 2117.66
Permanent Ineff=
       F       F
Bank Sta=315.72,335.1
XS Rating Curve= 0 ,0
Exp/Cntr(USF)=0,0
Exp/Cntr=0.3,0.1

Type RM Length L Ch R = 1 ,2434    ,186.4,184.3,179.5
XS GIS Cut Line= 4
2319373.82133223714111.1626707552319417.79175871714211.806574754
2319512.27870713714444.3686417832319595.77920727 714618.34097449
#Sta/Elev= 30
       0 2167.82    32.8 2151.38    45.9 2141.03    58.9 2139.39    63.3 2137.65
    80.8 2125.02    93.9 2117.09   115.6 2107.42     125 2106.33   145.9 2106.81
   177.2 2104.09   236.5 2103.37   253.8 2100.92   271.1 2101.47  284.44 2098.54
   296.8 2097.79   303.1 2098.53   309.9 2100.01   327.2 2099.97   353.1 2102.53
   364.4 2110.38   388.3 2131.79   400.4 2138.74   412.3 2151.44   442.3 2174.63
   446.1 2176.54   459.4 2177.96   468.2  2184.7   499.3 2197.59   553.8 2223.82
#Mann= 3 ,0,0
       0      .1       0  284.44    .045       0   303.1      .1       0
Bank Sta=284.44,303.1
XS Rating Curve= 0 ,0
Exp/Cntr(USF)=0,0
Exp/Cntr=0.3,0.1

Type RM Length L Ch R = 1 ,2249    ,210,210.5,210
XS GIS Cut Line= 4
2319195.64457493714213.296407193 2319218.0116098714322.646355462
2319395.70527574714500.3400213992319493.87170657714653.181426365
#Sta/Elev= 30
       0  2143.4      53 2125.07     106 2101.13   120.3 2097.25   148.6 2094.95
   154.8 2096.23     180 2095.91     200 2093.02   244.8 2094.68   256.1 2091.32
   261.8 2090.23   273.3 2091.29   290.6    2095   304.4 2095.27   321.4 2093.24
   335.3 2095.88   352.3 2096.04   358.2 2097.97   368.7 2104.68   378.2 2108.21
   387.7 2118.08   392.8 2121.19   430.4 2151.55   453.6 2163.93   468.5 2165.28
   479.6 2173.45   511.3 2188.95   520.8 2194.73   531.8 2197.54   544.6 2205.72
#Mann= 3 ,-1,0
       0      .1       0   256.1    .045       0   273.3      .1       0
#XS Ineff= 2 , 0
          246.93 2104.62  292.42         2106.79
Permanent Ineff=
       F       F
Bank Sta=256.1,273.3
XS Rating Curve= 0 ,0
Exp/Cntr(USF)=0,0
Exp/Cntr=0.3,0.1

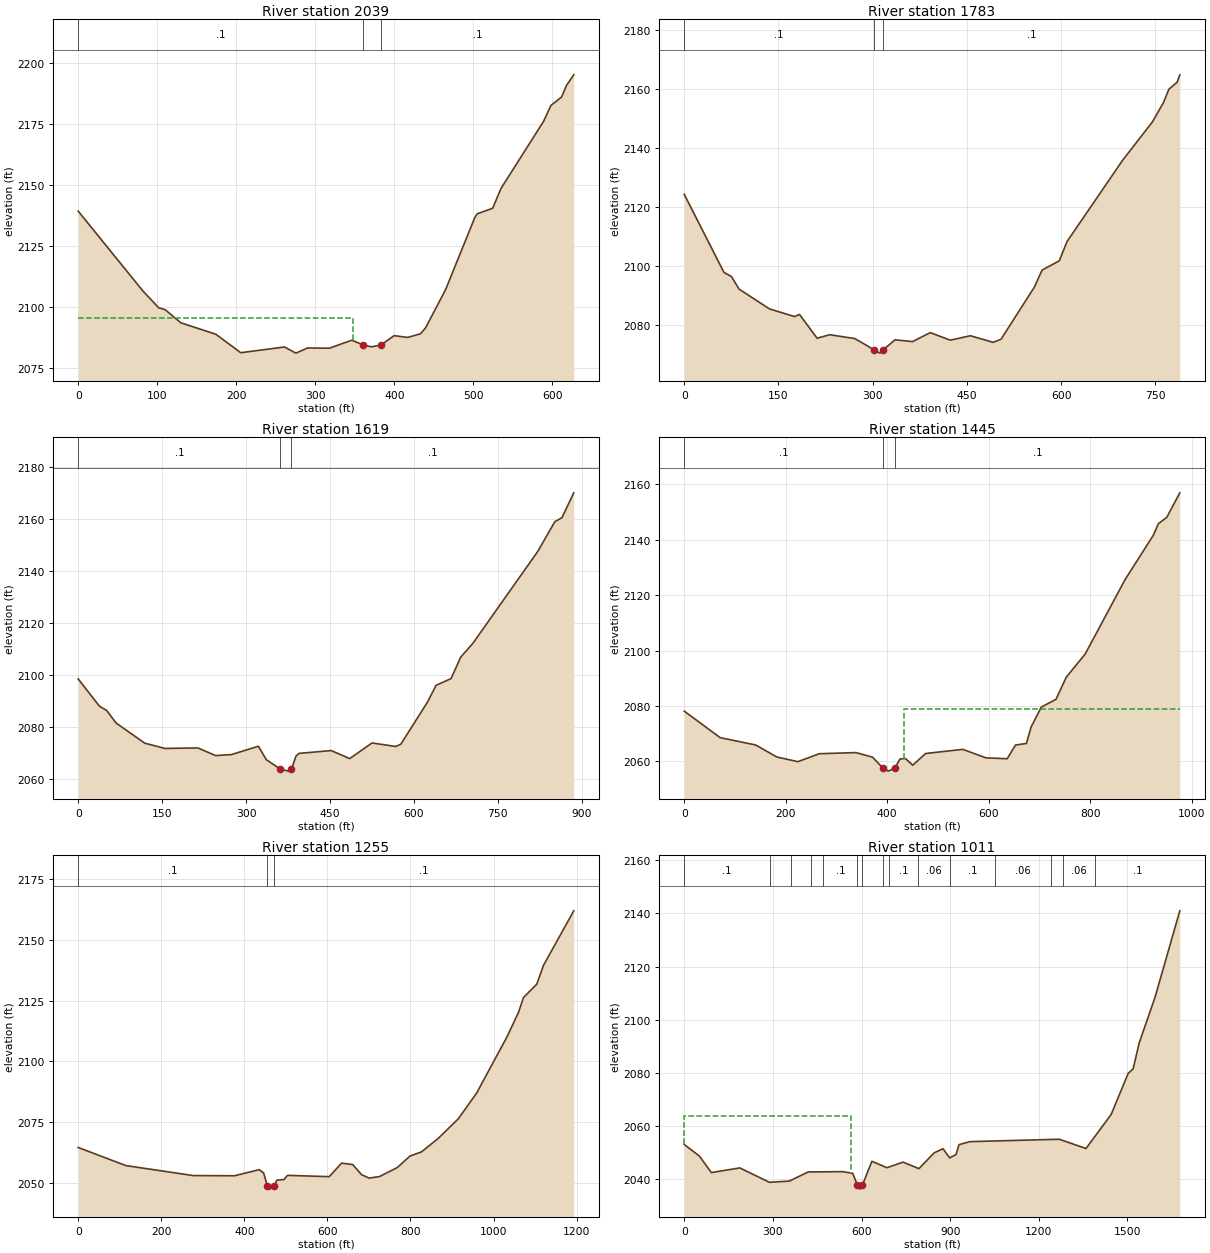
Type RM Length L Ch R = 1 ,2039    ,250.5,255.8,265.8
XS GIS Cut Line= 4
2319028.10196684714259.6144300952319042.97470637714437.647859412
2319218.94353729714621.4015479062319363.64027202714750.489314577
#Sta/Elev= 30
       0 2139.21    81.8 2106.51   101.9 2099.58   109.9 2098.85     130 2093.42
   174.2 2088.75   205.7 2081.18   261.1 2083.53   275.4 2081.01   290.3 2083.12
   317.8 2083.03   346.1  2086.3   360.8 2084.32   371.2  2083.6   382.9 2084.32
   382.9 2084.33   399.8 2088.17   416.8 2087.44   433.1 2088.95   439.5 2091.35
     465 2107.14   501.8 2136.56   504.8 2138.09   524.4 2140.39   534.9 2148.46
     589  2176.1   598.1 2182.51   611.6 2185.97   617.9 2190.77     627 2195.06
#Mann= 3 ,0,0
       0      .1       0   360.8    .045       0   382.9      .1       0
#XS Ineff= 2 , 0
          347.22 2095.52
Permanent Ineff=
       F       F
Bank Sta=360.8,382.9
XS Rating Curve= 0 ,0
Exp/Cntr(USF)=0,0
Exp/Cntr=0.3,0.1

Type RM Length L Ch R = 1 ,1783    ,169.8,164.2,157.1
XS GIS Cut Line= 4
2318952.72627939714306.2812337012318965.27551588714435.972460225
2318965.91187922 714809.849177292319228.24130057714920.303670491
#Sta/Elev= 30
       0 2124.19    63.2 2097.74    75.2 2096.31    87.3 2092.07   135.5 2085.38
   175.5 2082.76   183.5 2083.48   211.5 2075.42   231.5 2076.61   271.5  2075.3
   302.1 2071.51   311.5 2070.37  316.682071.491   335.5 2074.88   363.5 2074.28
   391.5 2077.32   423.5 2074.76   455.5 2076.27   491.5 2074.03   504.2 2075.06
   557.3 2092.74   569.5  2098.5     597 2101.66   609.2 2108.16   697.6 2135.69
   745.3 2148.77   762.7 2155.25   771.4 2159.82   784.4 2162.17   788.8  2164.7
#Mann= 3 ,-1,0
       0      .1       0   302.1    .045       0  316.68      .1       0
Bank Sta=302.1,316.68
XS Rating Curve= 0 ,0
Exp/Cntr(USF)=0,0
Exp/Cntr=0.3,0.1

Type RM Length L Ch R = 1 ,1619    ,175.9,174.3,173.5
XS GIS Cut Line= 4
2318713.26245791714365.6684248892318662.18027857714502.661542206
 2318968.6733546714834.6957079072319235.69383751 714941.50390107
#Sta/Elev= 30
       0 2098.45    37.9 2087.97    50.7 2086.35    67.8 2081.46     119 2073.72
   155.1 2071.69     214 2071.88   245.6 2068.95     274 2069.33   322.1 2072.54
   336.2 2067.38   361.4 2063.72   375.9 2062.96  381.13 2063.71   389.2 2068.72
   394.6 2069.79   452.3 2070.87   485.3 2067.79   525.2  2073.8   567.9 2072.44
   576.8 2073.37   624.2 2089.49   639.6 2095.96   666.5 2098.59   683.7 2106.85
   705.2 2112.08   821.6 2147.58   851.9 2158.96   864.6  2160.5   885.7 2170.07
#Mann= 3 ,-1,0
       0      .1       0   361.4    .045       0  381.13      .1       0
Bank Sta=361.4,381.13
XS Rating Curve= 0 ,0
Exp/Cntr(USF)=0,0
Exp/Cntr=0.3,0.1

Type RM Length L Ch R = 1 ,1445    ,188.3,189.6,189.7
XS GIS Cut Line= 4
2318607.39078669714440.5771228212318549.65756011714659.963383824
2318881.62361294714963.0628233692319173.17640717715035.229356593
#Sta/Elev= 30
       0 2078.15    70.9 2068.58   140.7 2065.95   182.6  2061.6     224 2059.93
   266.3  2062.8   338.6  2063.2   371.1 2061.55   390.9 2057.75   402.2 2056.52
  415.412057.723   425.3 2060.92   436.2 2061.03   450.3 2058.66   475.8 2062.88
     549 2064.37   594.7  2061.3   636.5 2060.99   652.8 2065.92   674.4  2066.5
   683.5 2072.36   703.7 2079.61   732.6 2082.39   752.9 2090.37   790.3 2098.77
   868.6 2125.49   924.7 2141.61   934.6 2145.76     951 2147.99   976.7 2156.85
#Mann= 3 ,-1,0
       0      .1       0   390.9    .045       0  415.41      .1       0
#XS Ineff= 2 , 0
                             433         2078.94
Permanent Ineff=
       F       F
Bank Sta=390.9,415.41
XS Rating Curve= 0 ,0
Exp/Cntr(USF)=0,0
Exp/Cntr=0.3,0.1

Type RM Length L Ch R = 1 ,1255    ,249.5,244.5,241.5
XS GIS Cut Line= 4
 2318532.4119648714533.0626652262318397.74164668714775.051974543
2318771.31038897715108.6819425422319184.61165817 715150.47645291
#Sta/Elev= 30
       0  2064.6   114.6 2057.15   276.9 2053.04   376.2 2052.95   435.7 2055.47
   446.5  2054.1  455.64 2048.69   461.5 2047.46471.27892048.663   478.6 2051.18
   495.5 2051.39     504 2053.12   604.4 2052.59   634.3 2058.16     661 2057.57
   682.4 2053.38   700.5 2052.01   725.3 2052.62   768.2 2056.33   798.8 2061.06
   826.5 2062.78   866.7  2068.3   915.4 2076.42   959.6 2087.06    1032 2109.95
  1060.1 2120.14  1072.2 2126.29  1104.3 2131.81  1120.4 2139.56  1193.2 2161.95
#Mann= 3 ,0,0
       0      .1       0  455.64    .045       0471.2789      .1       0
Bank Sta=455.64,471.2789
XS Rating Curve= 0 ,0
Exp/Cntr(USF)=0,0
Exp/Cntr=0.3,0.1

Type RM Length L Ch R = 1 ,1011    ,78.8,78.9,78.8
XS GIS Cut Line= 6
2318180.27030981714589.9851915392318147.41393125 714929.06508501
2318318.53652665715037.8634666412318694.68711997715188.788087414
 2318917.5472685 715531.606121332319225.63201508715454.581159241
#Sta/Elev= 30
       0 2053.11    51.4 2048.75    91.6 2042.54   188.1  2044.3   288.2 2038.89
   355.8 2039.34   419.5 2042.78   535.9 2042.89   570.2 2042.28 586.0092037.887
     595 2036.32603.32892037.934   635.1 2046.79   686.4 2044.37   740.4 2046.48
   794.5 2044.03   845.7 2049.94   875.9 2051.52   898.5 2048.08   919.8 2049.31
   930.1 2053.04   966.8 2054.18  1269.3 2055.08  1359.9  2051.6  1445.1  2064.4
  1502.8 2079.87  1519.3 2081.54  1539.9 2091.28  1593.5 2108.45  1677.4 2140.98
#Mann= 15 ,-1,0
       0      .1       0     290     .06       0  360.67      .1       0
  430.67     .06       0  470.67      .1       0 586.009    .045       0
603.3289      .1       0  673.45     .06       0  693.45      .1       0
  791.19     .06       0  901.19      .1       0 1050.99     .06       0
 1240.99      .1       0 1280.99     .06       0 1389.88      .1       0
#XS Ineff= 2 , 0
          565.34 2063.93
Permanent Ineff=
       F       F
Bank Sta=586.009,603.3289
XS Rating Curve= 0 ,0
Exp/Cntr(USF)=0,0
Exp/Cntr=0.3,0.1