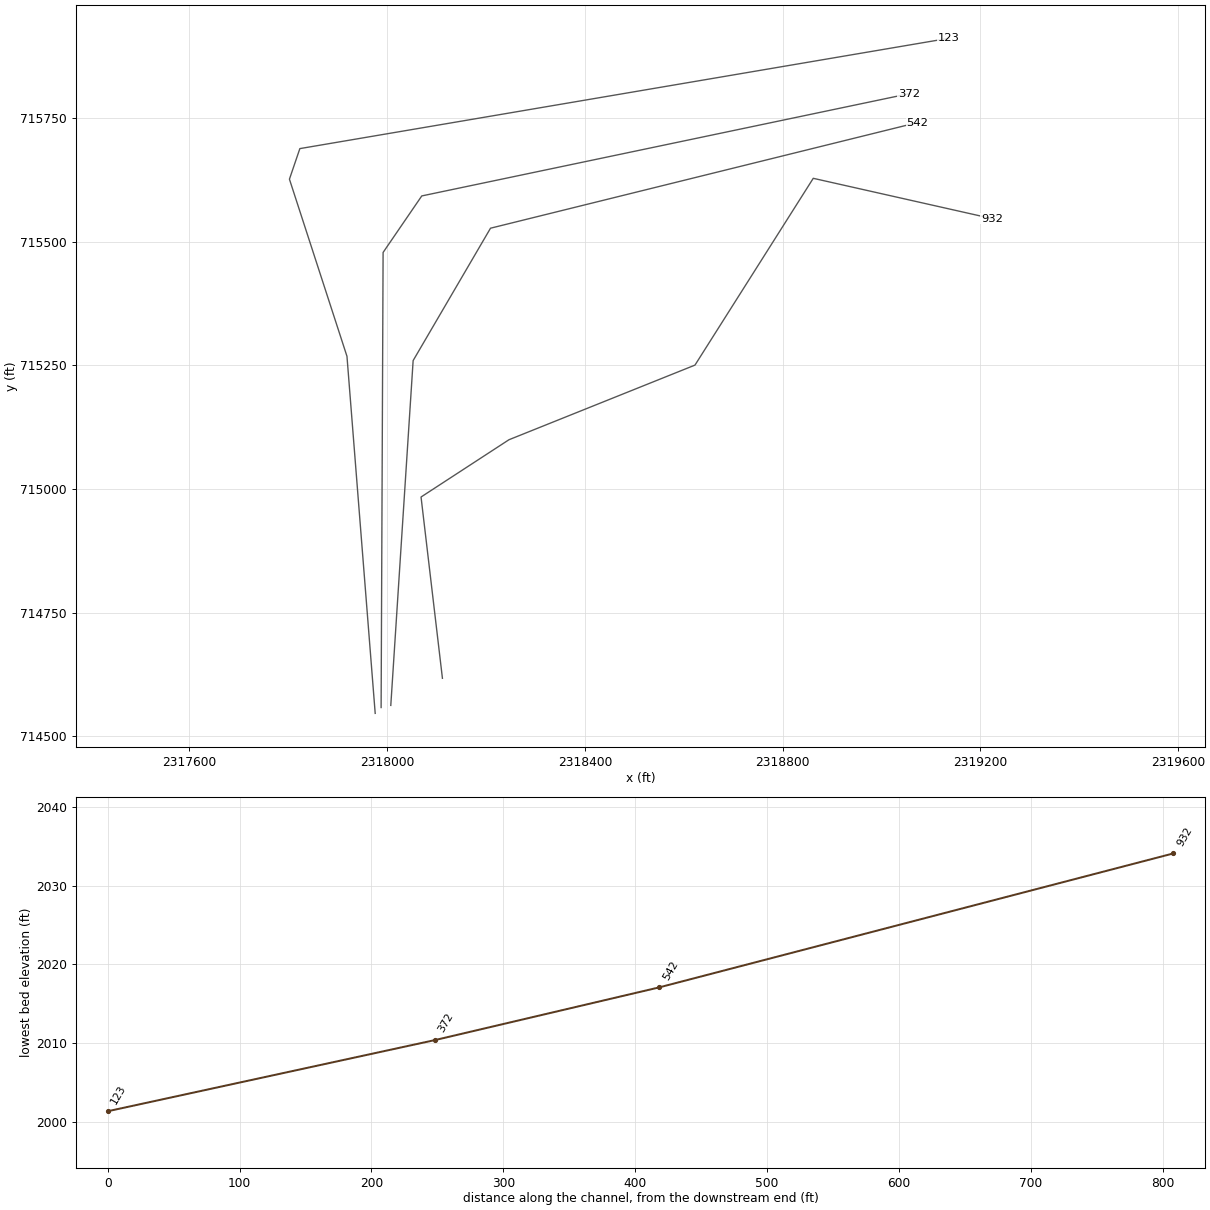
HEC-RAS study JOHNSRN.prj: JOHNSRN

--- JOHNSRN.g01 (geometry) --- (continued)

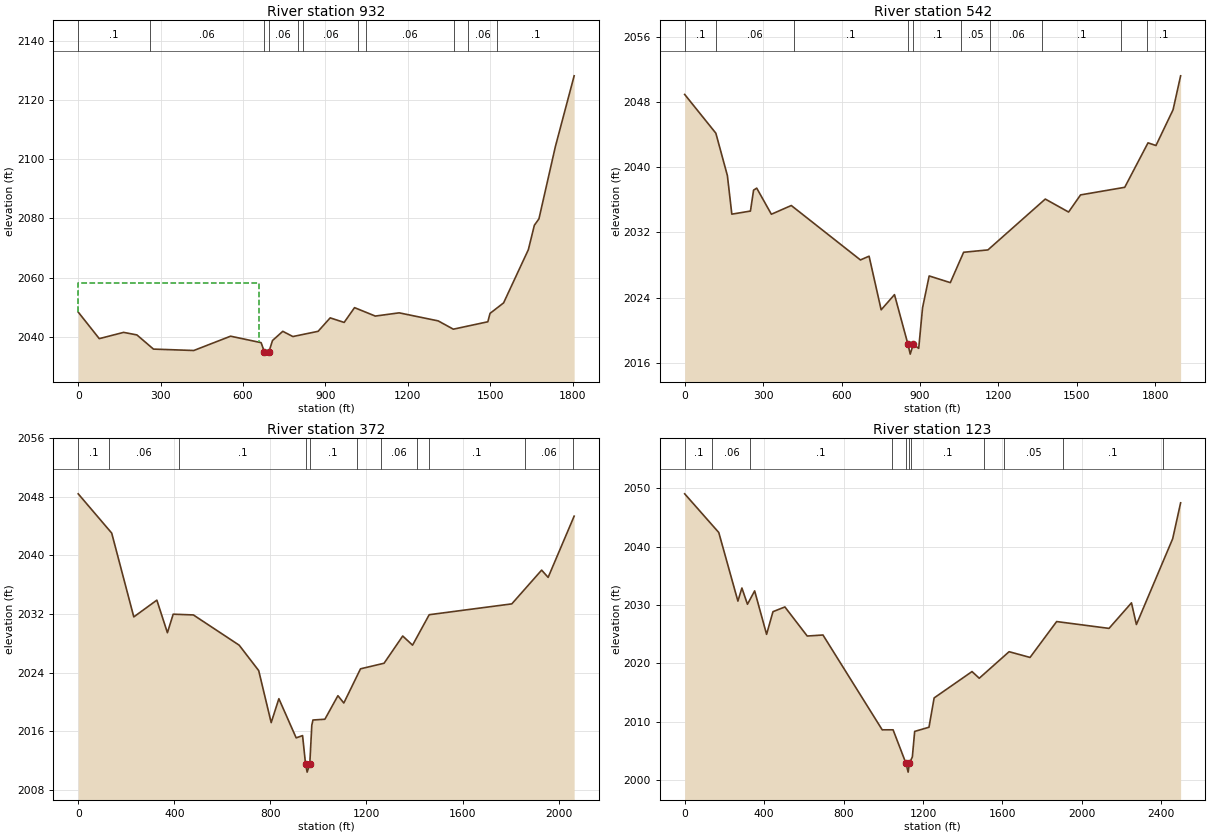
Type RM Length L Ch R = 1 ,932     ,381.4,390,395.5
XS GIS Cut Line= 6
2318111.98506056714616.995753038 2318068.7460165714983.565052152
2318246.55709213715099.3942735712318622.70768544715250.318894345
2318861.90877172715628.0461824162319222.90114186715546.705846314
#Sta/Elev= 30
       0  2048.3    76.7 2039.31   165.3 2041.43   213.7 2040.57   274.1 2035.77
   420.9  2035.3   554.9 2040.14   666.1 2037.95  677.87 2034.84   686.9 2034.07
   694.4 2034.85   707.6 2038.68     745 2041.79   781.7 2040.02   873.6 2041.79
   917.6 2046.34   968.4  2044.8  1006.3  2049.8  1081.9 2046.95  1168.8 2048.04
  1310.9 2045.32    1366 2042.51  1491.6 2045.02  1499.8 2047.87    1549  2051.4
  1639.2 2069.41  1661.1 2077.68  1677.8 2079.86  1737.6  2104.3    1806 2128.25
#Mann= 11 ,-1,0
       0      .1       0     260     .06       0  677.87    .045       0
   694.4     .06       0  799.07      .1       0  819.07     .06       0
 1018.86     .05       0 1048.86     .06       0 1368.86      .1       0
 1418.86     .06       0 1525.96      .1       0
#XS Ineff= 2 , 0
          658.48 2058.07
Permanent Ineff=
       F       F
Bank Sta=677.87,694.4
XS Rating Curve= 0 ,0
Exp/Cntr(USF)=0,0
Exp/Cntr=0.3,0.1

Type RM Length L Ch R = 1 ,542     ,170.2,170.1,169.1
XS GIS Cut Line= 4
2318007.56597983714562.1400171592318052.76266004715259.492065336
2318209.23133617715527.1642675552319071.79095115715740.563202024
#Sta/Elev= 30
       0 2048.91   119.3 2044.16   163.4 2038.97   180.4 2034.24   251.6 2034.62
   263.6 2037.18   275.6 2037.43   331.7 2034.23   407.9  2035.3   672.4 2028.63
   705.5 2029.09   751.7 2022.52   802.7 2024.38  854.35 2018.28   862.9 2017.09
  874.42 2018.28   895.4  2017.8   910.1 2022.77   935.4 2026.67  1016.3 2025.85
  1067.2 2029.57  1160.2 2029.86  1379.6 2036.09  1468.8  2034.5  1514.6  2036.6
  1683.6 2037.53  1772.7 2042.98  1803.1 2042.65  1868.5 2047.03  1897.4 2051.19
#Mann= 10 ,-1,0
       0      .1       0     120     .06       0     420      .1       0
  854.35    .045       0  874.42      .1       0 1058.86     .05       0
 1168.86     .06       0 1368.86      .1       0 1668.86     .06       0
 1768.86      .1       0
Bank Sta=854.35,874.42
XS Rating Curve= 0 ,0
Exp/Cntr(USF)=0,0
Exp/Cntr=0.3,0.1

Type RM Length L Ch R = 1 ,372     ,245,248.2,249.7
XS GIS Cut Line= 4
2317987.99682469714557.8285989082317992.00690186  715478.1413085
2318070.20340659 715592.428507732319054.67735084715798.947481778
#Sta/Elev= 30
       0 2048.42   139.4 2043.06   231.4 2031.61   327.4  2033.9   371.4 2029.45
   395.4 2031.98   479.4 2031.88   670.1 2027.75   751.4 2024.28   803.4 2017.17
   835.4 2020.44   907.4 2015.09   934.1  2015.4  946.37 2011.53   953.1 2010.41
   964.12011.535   972.5 2016.81   977.3 2017.53  1026.9 2017.63  1081.2 2020.85
  1105.8 2019.85  1175.3 2024.52  1273.3 2025.28    1351    2029  1391.9 2027.75
  1461.3 2031.91  1805.2 2033.39  1929.3    2038  1956.4 2037.01  2064.7 2045.37
#Mann= 11 ,-1,0
       0      .1       0     130     .06       0     420      .1       0
  946.37    .045       0   964.1      .1       0  1158.8     .05       0
  1258.8     .06       0  1408.8     .05       0  1458.8      .1       0
  1858.8     .06       0  2058.8      .1       0
Bank Sta=946.37,964.1
XS Rating Curve= 0 ,0
Exp/Cntr(USF)=0,0
Exp/Cntr=0.3,0.1

Type RM Length L Ch R = 1 ,123     ,,,
XS GIS Cut Line= 5
2317976.03395999714546.0191343112317918.94440348 715268.12117981
2317802.60191966715626.3050492462317823.67382768715688.123241281
2319135.55508711 715911.12383283
#Sta/Elev= 30
       0 2049.02   171.7  2042.4     268 2030.66   288.1  2032.9   316.1 2030.12
   352.3 2032.41   412.4 2024.97   444.5 2028.85   504.6 2029.66   617.1 2024.68
   696.3 2024.86   994.6 2008.63  1049.3 2008.63  1113.9 2002.92  1125.1 2001.39
 1131.57 2002.91  1146.3 2003.99    1158 2008.36    1230 2009.07    1256 2014.09
  1446.7  2018.6  1483.2 2017.46  1633.4    2022  1738.9 2021.02  1872.8 2027.16
  2136.5 2025.99  2249.6 2030.36  2274.4 2026.65    2457 2041.33    2497 2047.48
#Mann= 11 ,-1,0
       0      .1       0     140     .06       0     330      .1       0
 1044.36     .06       0  1113.9    .045       0 1131.57     .06       0
 1140.96      .1       0 1506.27     .06       0 1606.27     .05       0
 1906.27      .1       0 2406.27     .06       0
Bank Sta=1113.9,1131.57
XS Rating Curve= 0 ,0
Exp/Cntr(USF)=0,0
Exp/Cntr=0.3,0.1
LCMann Table=0

Chan Stop Cuts=-1
Use User Specified Reach Order=0
Composite Channel Slope=5